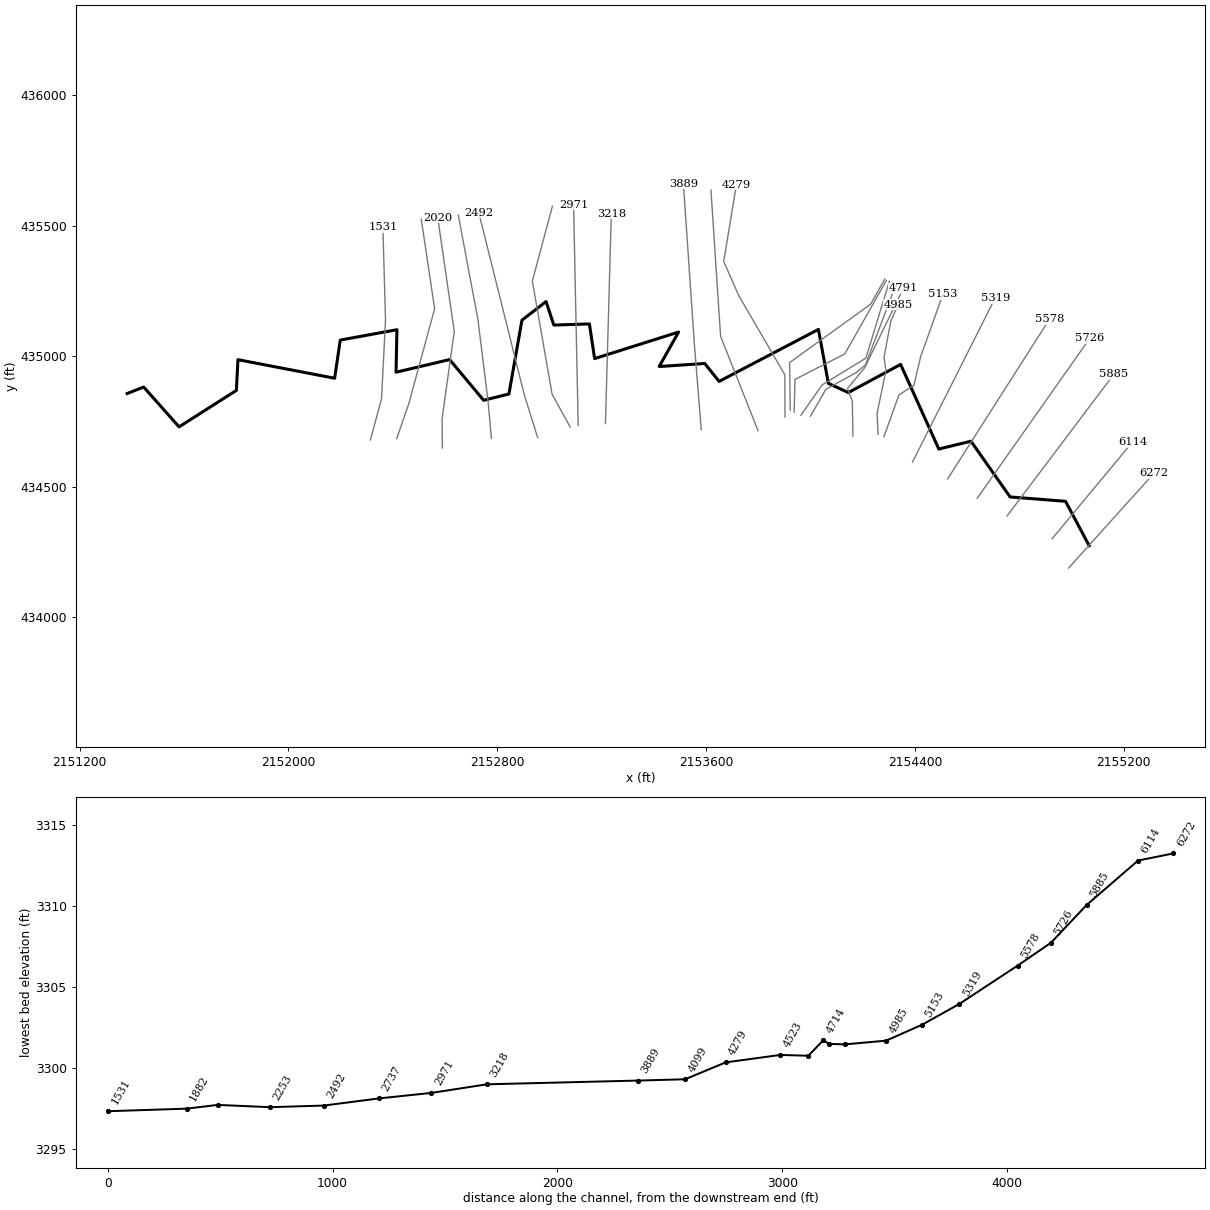
--- NFCHRYRV.prj (project) ---

Proj Title=NFCHRYRV
Current Plan=p01
Default Exp/Contr=0,0
English Units
Geom File=g01
Flow File=f01
Plan File=p01
Background Map Layer=Inundation Boundary (01pct Value_0)
BEGIN DESCRIPTION:
----------MODEL BY WOOD PLC 2021----------
Stream Name: North Fork Cherry River
Flood Zone: Enhanced Approximate
Pocahontas County, WV
HEC-RAS Version: RAS 6.1
Vertical Datum: NAVD88
Projection: NAD 1983 StatePlane West Virginia S FIPS 4702 (US Feet)
Terrain: 1-meter LIDAR (FEMA Region III 3DEP collected 2016-2018)
Land Use: 2019 NLCD
Hydrologic Method:
WV SIR2010-5033 regression equations
Model Notes:
KWSEL Tie-In to Greenbrier County Boundary
END DESCRIPTION:
DSS Export Rating Curves= 0
DSS Export Rating Curve Sorted= 0
DSS Export Volume Flow Curves= 0
DXF OffsetX= 0
DXF OffsetY= 0
DXF ScaleX= 0
DXF ScaleY= 0

--- NFCHRYRV.p01 (plan) ---

Plan Title=Floodplain
Program Version=6.00
Short Identifier=Floodplain
Geom File=g01
Flow File=f01
Subcritical Flow
K Sum by GR= 0
Std Step Tol= 0.01
Critical Tol= 0.01
Num of Std Step Trials= 20
Max Error Tol= 0.3
Flow Tol Ratio= 0.001
Split Flow NTrial= 30
Split Flow Tol= 0.02
Split Flow Ratio= 0.02
Log Output Level= 0
Friction Slope Method= 1
Unsteady Friction Slope Method= 2
Unsteady Bridges Friction Slope Method= 1
Parabolic Critical Depth
Global Vel Dist= 0 , 0 , 0
Global Log Level= 0
CheckData=True
Encroach Param=-1 ,0,0, 0
Mapping Interval=1HOUR
Computation Time Step Use Courant=        0
Computation Time Step Use Time Series=    0
Computation Time Step Count To Double=0
Computation Time Step Max Doubling=0
Computation Time Step Max Halving=0
Computation Time Step Residence Courant=0
Run HTab= 0
Run UNet= 0
Run Sediment= 0
Run PostProcess= 0
Run WQNet= 0
Run RASMapper=-1
UNET Theta= 0
UNET Theta Warmup= 0
UNET ZTol= 0
UNET ZSATol= 0
UNET MxIter= 0
UNET Max Iter WO Improvement= 0
UNET MaxInSteps= 0
UNET DtIC= 0
UNET DtMin= 0
UNET MaxCRTS= 0
UNET WFStab= 0
UNET SFStab= 0
UNET WFX= 1
UNET SFX= 1
UNET Gravity=32.174
UNET 1D Methodology=Finite Difference
UNET DSS MLevel= 1
UNET Pardiso=0
UNET DZMax Abort= 0
UNET Use Existing IB Tables= 0
UNET Froude Reduction=False
UNET Froude Limit= 0
UNET Froude Power= 0
UNET D1 Cores= 0
UNET WindReference=Eulerian
UNET WindDragFormulation=Hsu (1988)
UNET D2 Coriolis=0
UNET D2 Cores= 0
UNET D2 Theta= 1
UNET D2 Theta Warmup= 1
UNET D2 Z Tol= 0.01
UNET D2 Volume Tol= 0.01
UNET D2 Max Iterations= 20
UNET D2 Equation= 0
UNET D2 RampUpFraction=0.1
UNET D2 TimeSlices= 1
UNET D2 Turbulence Formulation=Non-Conservative (original)
UNET D2 Eddy Viscosity=0.3
UNET D2 Transverse Eddy Viscosity=0.1
UNET D2 Smagorinsky Mixing=0
UNET D2 BCVolumeCheck=0
UNET D2 Cores=0
UNET D2 SolverType=PARDISO (Direct)
UNET D2 Minimum Iterations= 2147483647
UNET D2 Maximum Iterations= 2147483647
UNET D2 Restart Number= 10
UNET D2 Relaxation Coeff=1.3
UNET D2 SOR Precondition Iterations= 10
UNET D2 ILUT Maximum Fill= 8
UNET D2 ILUT Tolerance=1E-08
UNET D1D2 MaxIter= 0
UNET D1D2 ZTol=0.01
UNET D1D2 QTol=0.1
UNET D1D2 MinQTol=1
Write IC File= 0
Write IC File at Fixed DateTime=0
Write IC File at Sim End=0
Echo Input=False
Echo Parameters=False
Echo Output=False
Write Detailed= 0
HDF Write Warmup=0
HDF Write Time Slices=0
HDF Flush=0
HDF Compression= 1
HDF Chunk Size= 1
HDF Spatial Parts= 1
HDF Use Max Rows=0
HDF Fixed Rows= 1
Calibration Method= 0
Calibration Iterations= 20
Calibration Max Change=0.05
Calibration Tolerance=0.2
Calibration Maximum=1.5
Calibration Minimum=0.5
Calibration Optimization Method= 1
WQ AD Non Conservative
WQ ULTIMATE=-1
WQ Max Comp Step=1HOUR
WQ Output Interval=15MIN
WQ Output Selected Increments= 0
WQ Output face flow=0
WQ Output face velocity=0
WQ Output face area=0
WQ Output face dispersion=0
WQ Output cell volume=0
WQ Output cell surface area=0
WQ Output cell continuity=0
WQ Output cumulative cell continuity=0
WQ Output face conc=0
WQ Output face dconc_dx=0
WQ Output face courant=0
WQ Output face peclet=0
WQ Output face adv mass=0
WQ Output face disp mass=0
WQ Output cell mass=0
WQ Output cell source sink temp=0
WQ Output nsm pathways=0
WQ Output nsm derived pathways=0
WQ Create Restart=0
WQ Fixed Restart=0
WQ System Summary=0
WQ Write To DSS=0
Sorting and Armoring Iterations= 10
XS Update Threshold= 0.02
Bed Roughness Predictor= 0
Hydraulics Update Threshold= 0.02
Energy Slope Method= 1
Volume Change Method= 1
Sediment Retention Method= 0
Sediment TS Multiplier= 1
Warm Up Method= 0
XS Weighting Method= 0
Number of US Weighted Cross Sections= 1
Number of DS Weighted Cross Sections= 1
Upstream XS Weight=0
Main XS Weight=1
Downstream XS Weight=0
Number of DS XS's Weighted with US Boundary= 1
Upstream Boundary Weight= 1
Weight of XSs Associated with US Boundary= 0
Number of US XS's Weighted with DS Boundary= 1
Downstream Boundary Weight= 0.5
Weight of XSs Associated with DS Boundary= 0.5
Percentile Method= 0
Sediment Output Level= 3
Mass or Volume Output= 0
Output Increment Type= 1
Profile and TS Output Increment= 1
Transport Output Increment 1
XS Output Flag= 0
XS Output Increment= 10
Read HDF5 Sediment Hotstart= 0
Sediment Hotstart Type= 0
Write Gradation File= 0
Read Gradation Hotstart= 0
Write HDF5 File= 1
Write Binary Output= 1
Write DSS Sediment File= 0
DSS Sediment Output Type= 1
SV Curve= 0
Specific Gage Flag= 0
Subcell Erosion Methods= 0
Subcell Deposition Methods= 0
Advection Scheme= 1
Matrix Solver= 0
Implicit Weighting Factor= 1
Maximum Outer Loop Convergence Iterations= 5
Convergence Maximum Absolute= 0.001
Convergence RMSE= 0.0001
Grain Fractions Max Abs Error= 0.001
Max Subgrid Regions= 1
Max Subgrid Length Scale= 3.402823E+38
Initial Layer Thickness= 3.402823E+38
Min Layer Thickness= 3.402823E+38
Max Layer Thickness= 3.402823E+38
Number of Layers= 5

--- NFCHRYRV.f01 (steady flow) ---

Flow Title=Flow
Program Version=6.10
Number of Profiles= 6
Profile Names=01pct,10pct,04pct,02pct,0_2pct,01plus
River Rch & RM=NFCHRYRV,Main            ,6272
     812     435     574     689    1130    1200
Boundary for River Rch & Prof#=NFCHRYRV,Main            , 1
Up Type= 0
Dn Type= 1
Dn Known WS=3298.7
Boundary for River Rch & Prof#=NFCHRYRV,Main            , 2
Up Type= 0
Dn Type= 1
Dn Known WS=3297
Boundary for River Rch & Prof#=NFCHRYRV,Main            , 3
Up Type= 0
Dn Type= 1
Dn Known WS=3297.6
Boundary for River Rch & Prof#=NFCHRYRV,Main            , 4
Up Type= 0
Dn Type= 1
Dn Known WS=3298.2
Boundary for River Rch & Prof#=NFCHRYRV,Main            , 5
Up Type= 0
Dn Type= 1
Dn Known WS=3299.8
Boundary for River Rch & Prof#=NFCHRYRV,Main            , 6
Up Type= 0
Dn Type= 1
Dn Known WS=3300.2
DSS Import GetInterval= 0
DSS Import GetPeak= 0
DSS Import FillOption= 0

--- NFCHRYRV.g01 (geometry) ---

Geom Title=Geometry
Program Version=6.10

River Reach=NFCHRYRV        ,Main
Reach XY= 30
2155067.87400001434273.8369999982154977.45200004434443.746000022
2154765.01900001434460.5080000162154615.01700002434673.965000004
2154491.88600004434644.0830000192154345.43500003434968.239999995
2154145.14329655434860.2858006412154068.74100001434895.678000018
2154030.54600531 435102.32307443     2153650.017434903.084000006
2153595.01800002434971.7569999992153420.37400004      434960.147
2153494.78200005 435092.255000012153173.00000004434990.497000009
2153153.09300002435123.253000021     2153016.661435119.038000017
 2152986.8993243435209.0527954252152894.54000001435137.787000015
2152844.65600003434854.8910000182152747.75800005434830.770999998
2152617.43800001434986.7890000052152412.07400005434938.294000015
2152415.54919162435101.1613702922152198.38399999435061.414000005
2152176.81000002434915.2510000172151806.34199999434986.395999998
2151800.40099999434868.7039999962151580.72899999434728.978000015
2151445.10400003434881.5400000072151381.76247477434856.628364954

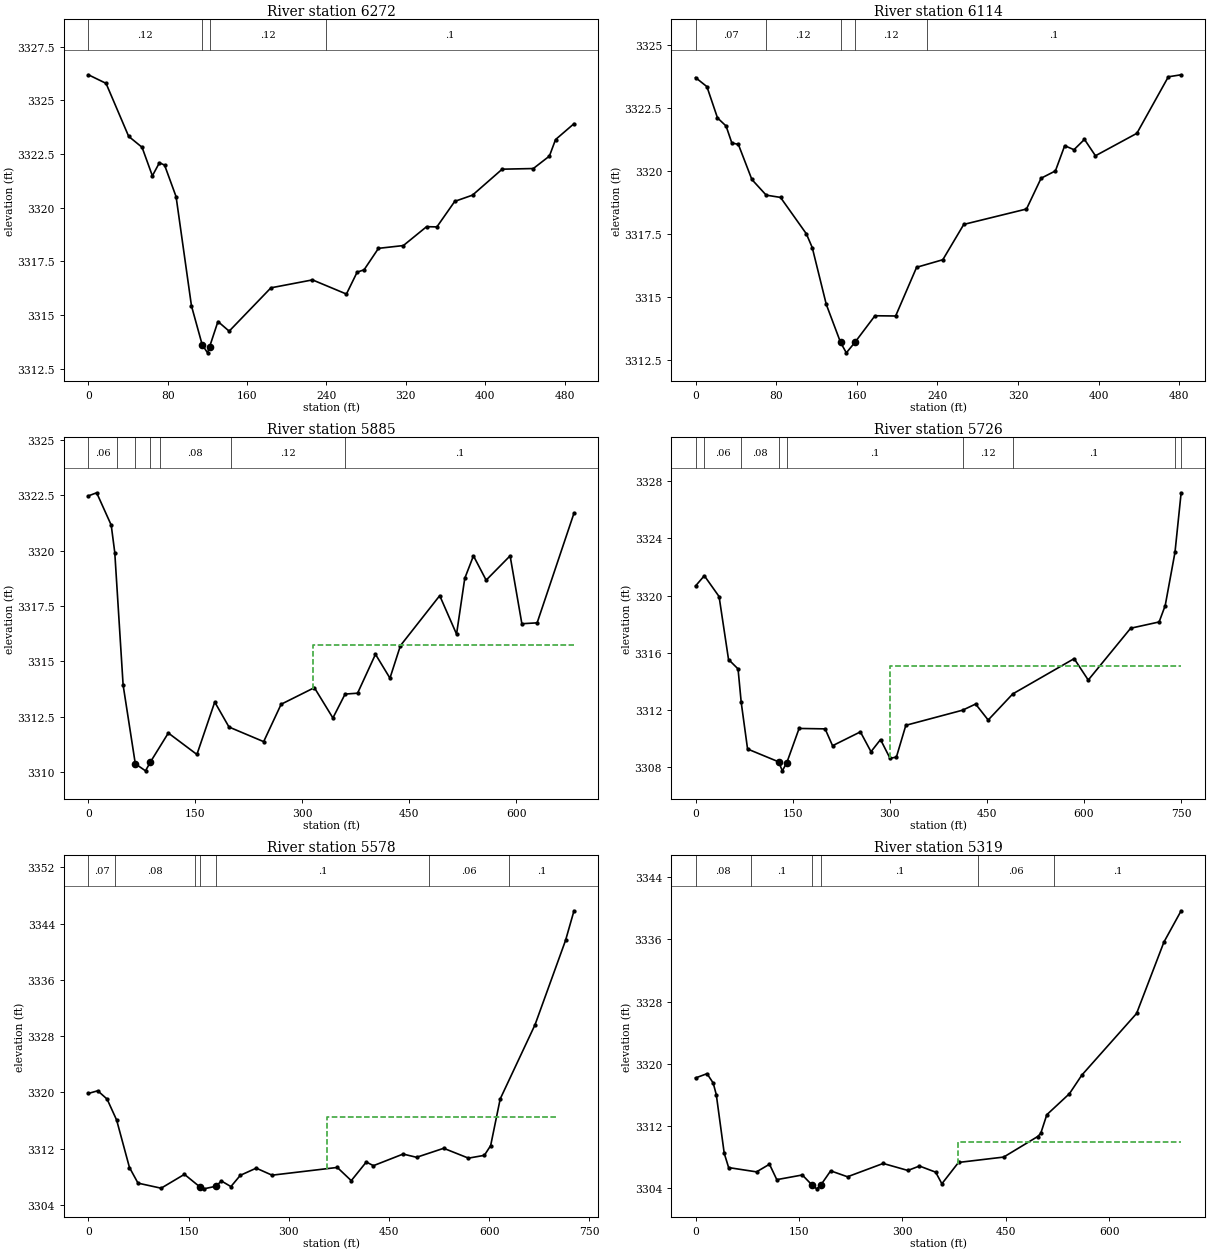
Type RM Length L Ch R = 1 ,6272    ,157.4,157.4,157.4
XS GIS Cut Line= 2
2154988.97950621434187.9551135242155316.66364124434551.612528968
#Sta/Elev= 30
       0 3326.19    17.8 3325.79    40.6 3323.32    54.1 3322.81    64.5 3321.48
    71.6 3322.09    76.8 3321.98    88.4 3320.51   103.9 3315.42   114.7 3313.61
   120.1 3313.23   122.1  3313.5   130.6 3314.69   141.9 3314.24     184 3316.26
   225.9 3316.63   260.1 3315.97   270.9 3316.99   277.9  3317.1   292.4  3318.1
   317.5 3318.23   340.9 3319.11   351.3  3319.1   369.3 3320.29   387.2 3320.58
   417.1 3321.79   448.5 3321.82   464.7  3322.4   470.9 3323.17   489.5 3323.91
#Mann= 4 ,-1,0
       0     .12       0   114.7    .045       0   122.1     .12       0
     240      .1       0
Bank Sta=114.7,122.1
XS Rating Curve= 0 ,0
Exp/Cntr(USF)=0,0
Exp/Cntr=0.3,0.1

Type RM Length L Ch R = 1 ,6114    ,234.2,228.9,231.2
XS GIS Cut Line= 2
2154926.14347084 434300.49749208 2155234.0494092 434670.99414577
#Sta/Elev= 30
       0  3323.7    11.3 3323.34    21.8  3322.1    30.3 3321.78      36 3321.11
    42.5 3321.05    55.9 3319.66    70.1 3319.04    84.3 3318.95   109.9 3317.51
   115.8 3316.96   129.7 3314.71   143.9  3313.2   149.6 3312.79   158.2 3313.21
     178 3314.26   198.5 3314.25   219.3 3316.18   245.3 3316.48   266.1 3317.88
   328.3 3318.49   342.8 3319.71     357    3320   366.2    3321   375.4 3320.84
   385.8 3321.25   396.7  3320.6   437.8 3321.49     469 3323.73   481.7 3323.81
#Mann= 5 ,-1,0
       0     .07       0      70     .12       0   143.9    .045       0
   158.2     .12       0     230      .1       0
Bank Sta=143.9,158.2
XS Rating Curve= 0 ,0
Exp/Cntr(USF)=0,0
Exp/Cntr=0.3,0.1

Type RM Length L Ch R = 1 ,5885    ,158.9,158.9,161.6
XS GIS Cut Line= 2
 2154753.4855085434387.6581691972155163.29142467434931.544315475
#Sta/Elev= 30
       0 3322.48    11.6 3322.62      32 3321.16      37 3319.92    48.7 3313.93
    65.8 3310.37    80.1 3310.05      87 3310.45   112.1 3311.76   152.2 3310.79
   177.2 3313.16   197.2 3312.03   245.8 3311.37   270.3 3313.06   316.9 3313.81
   342.9 3312.44     360 3313.52   377.5 3313.56   402.6 3315.32   422.9 3314.24
   437.6 3315.71   492.7 3317.97   516.3 3316.23   527.8 3318.75     540 3319.77
   557.8 3318.67   591.4 3319.77   607.9  3316.7   629.3 3316.74     681  3321.7
#Mann= 7 ,-1,0
       0     .06       0      40     .12       0    65.8    .045       0
      87     .12       0     100     .08       0     200     .12       0
     360      .1       0
#XS Ineff= 2 , 0
                          314.31         3315.73
Permanent Ineff=
       F       F
Bank Sta=65.8,87
XS Rating Curve= 0 ,0
Exp/Cntr(USF)=0,0
Exp/Cntr=0.3,0.1

Type RM Length L Ch R = 1 ,5726    ,148.5,148.5,152.3
XS GIS Cut Line= 2
2154638.99117036434455.4456192972155070.72666344435068.909340878
#Sta/Elev= 30
       0 3320.67    13.6 3321.39    36.4 3319.93      51 3315.52    65.7 3314.86
    70.6 3312.51    80.4 3309.25   128.4 3308.35   134.1 3307.72   141.1  3308.3
     160 3310.69   200.2 3310.66   211.7 3309.48   254.7 3310.45   271.1 3309.06
   285.8 3309.91   300.5  3308.6   310.3 3308.68   324.9 3310.91   412.6 3311.97
   432.7  3312.4   452.1 3311.28   490.1 3313.11   584.9 3315.58   606.7 3314.08
   672.2 3317.71   716.2 3318.15   725.6  3319.3   740.7 3323.03   750.2  3327.2
#Mann= 9 ,-1,0
       0     .07       0    13.6     .06       0    70.6     .08       0
   128.4    .045       0   141.1      .1       0   412.6     .12       0
   490.1      .1       0   740.7     .06       0   750.2      .1       0
#XS Ineff= 2 , 0
                             300         3315.07
Permanent Ineff=
       F       F
Bank Sta=128.4,141.1
XS Rating Curve= 0 ,0
Exp/Cntr(USF)=0,0
Exp/Cntr=0.3,0.1

Type RM Length L Ch R = 1 ,5578    ,258.9,258.9,258.9
XS GIS Cut Line= 2
2154525.40625046434529.3499346362154916.41863135 435142.34208424
#Sta/Elev= 30
       0 3319.86      14 3320.24      28 3319.06    42.3 3316.08    61.5 3309.34
    74.3 3307.12   108.9  3306.4   143.8 3308.37     167 3306.58   172.8 3306.31
   191.1 3306.68   199.1 3307.43   213.4 3306.63   227.5 3308.23   251.3 3309.25
     275 3308.25   372.7 3309.35   393.6 3307.47   416.1 3310.12   426.8  3309.6
   471.2 3311.25   491.4 3310.79     532 3312.07   569.1 3310.67   592.9 3311.07
   602.3 3312.45   616.6 3319.08   668.8 3329.63   714.5 3341.62   727.1 3345.81
#Mann= 7 ,-1,0
       0     .07       0      40     .08       0     160      .1       0
     167    .045       0   191.1      .1       0     510     .06       0
     630      .1       0
#XS Ineff= 1 ,-1
  357.41   700.83316.557
Permanent Ineff=
       F
Bank Sta=167,191.1
XS Rating Curve= 0 ,0
Exp/Cntr(USF)=0,0
Exp/Cntr=0.3,0.1

Type RM Length L Ch R = 1 ,5319    ,168.6,165.8,168.6
XS GIS Cut Line= 2
2154391.15696165434594.276077724 2154707.9474271435222.907157586
#Sta/Elev= 30
       0 3318.19    16.7 3318.74    25.6 3317.54    30.1 3316.05    41.6 3308.52
      48 3306.68    88.4 3306.13   107.2 3307.11   117.8 3305.13   154.8 3305.73
     169 3304.43   175.7 3303.95   181.6 3304.44   195.9 3306.26   220.3  3305.5
     272 3307.21   307.8 3306.31   324.6 3306.88   348.1 3306.09   357.1  3304.6
   381.2 3307.34   446.7 3308.03     496 3310.67   500.4 3311.07   509.2 3313.47
     542 3316.17   559.9 3318.55   639.3 3326.47     679 3335.65   703.9 3339.66
#Mann= 6 ,-1,0
       0     .08       0      80      .1       0     169    .045       0
   181.6      .1       0     410     .06       0     520      .1       0
#XS Ineff= 2 , 0
                             380            3310
Permanent Ineff=
       F       F
Bank Sta=169,181.6
XS Rating Curve= 0 ,0
Exp/Cntr(USF)=0,0
Exp/Cntr=0.3,0.1

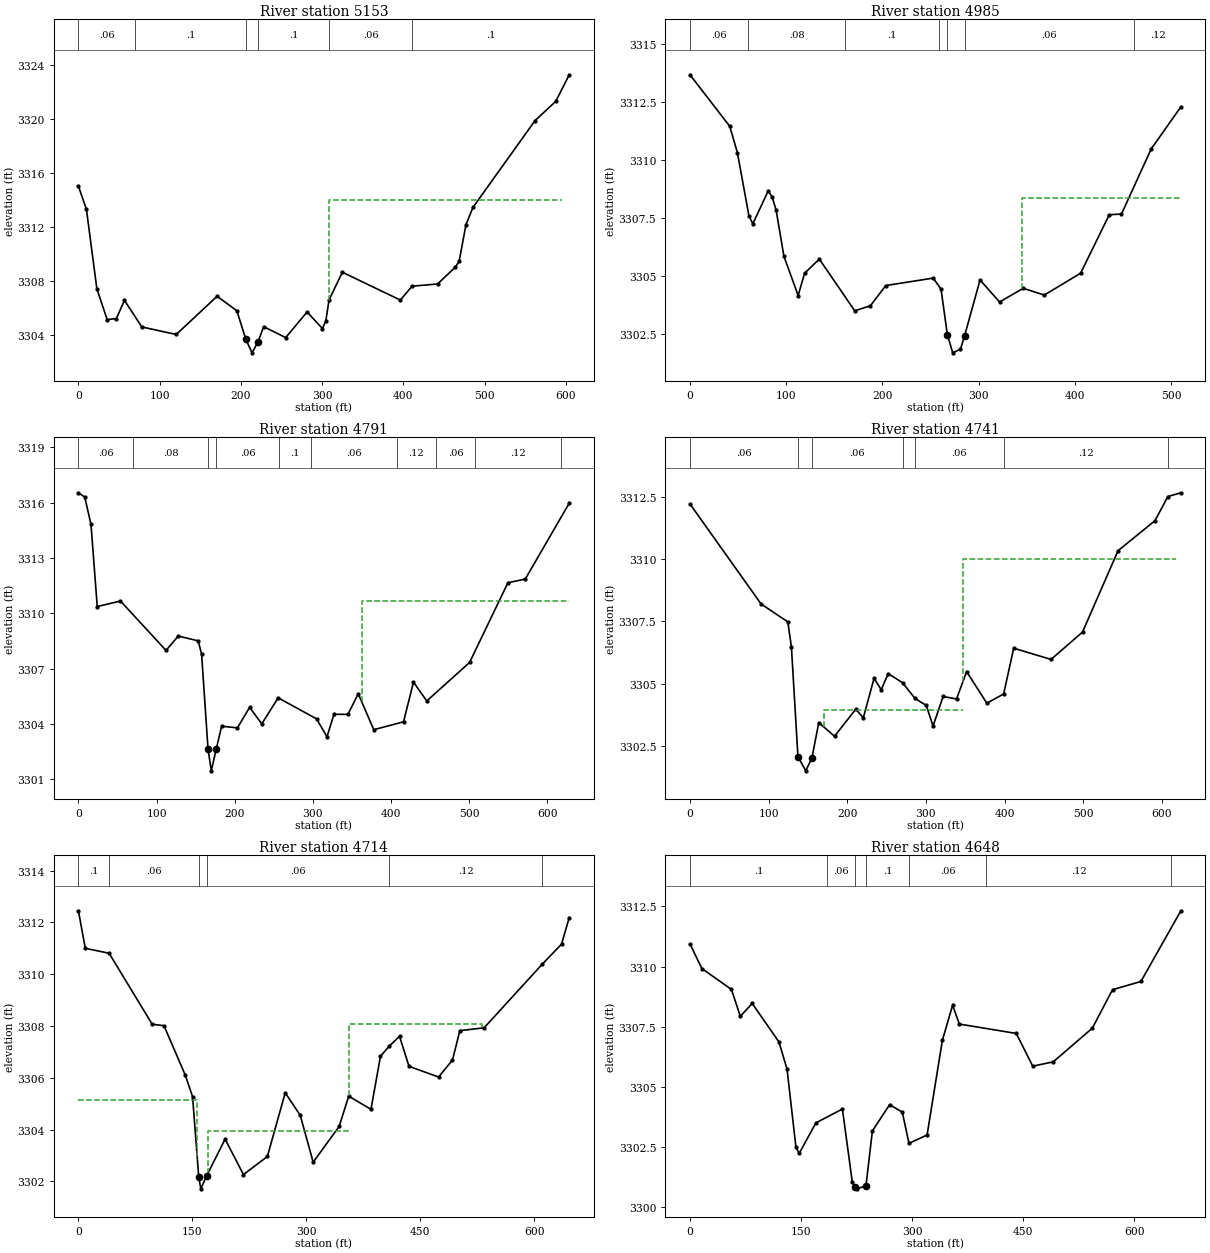
Type RM Length L Ch R = 1 ,5153    ,145.8,159.7,176.5
XS GIS Cut Line= 5
2154281.78275488 434691.83027749 2154338.9995597434851.200933912
2154396.74685399434888.782506388 2154422.3678309434998.298963742
2154507.72160652  435236.8952764
#Sta/Elev= 30
       0 3315.02     9.9  3313.3    22.7 3307.42    35.4 3305.13    46.7 3305.21
    56.7 3306.56      78 3304.59   120.4 3304.03   170.7 3306.86     195 3305.79
206.01583303.676   213.7 3302.67221.04523303.484     228 3304.61   255.1  3303.8
   281.4  3305.7   300.3 3304.47   304.4 3305.01   308.5  3306.6   324.9 3308.64
   396.2 3306.58   410.7 3307.61     442 3307.77   463.9 3309.02   468.5 3309.44
     477 3312.17   485.5 3313.44   561.9 3319.87   587.4  3321.3   604.1 3323.27
#Mann= 6 ,-1,0
       0     .06       0      70      .1       0206.0158    .045       0
221.0452      .1       0  308.23     .06       0   410.7      .1       0
#XS Ineff= 1 ,-1
  308.28   594.6 3313.97
Permanent Ineff=
       F
Bank Sta=206.0158,221.0452
XS Rating Curve= 0 ,0
Exp/Cntr(USF)=0,0
Exp/Cntr=0.3,0.1

Type RM Length L Ch R = 1 ,4985    ,180.6,184.1,189.2
XS GIS Cut Line= 6
2154258.89349205434699.962618284 2154255.4255159 434781.11326018
2154289.41168216434945.4953296622154281.78213463434995.434186214
2154308.13875337 435134.846827422154336.57615779 435197.27039811
#Sta/Elev= 30
       0 3313.67    41.3 3311.45    49.3 3310.31    61.2  3307.6    65.3 3307.25
    81.3 3308.67    85.4  3308.4    89.5 3307.84    97.6 3305.85   112.4 3304.16
   119.1 3305.12   134.4 3305.73   171.2  3303.5   187.5 3303.72   203.5 3304.59
   252.8 3304.91   260.9 3304.43   267.4 3302.48     273 3301.69   281.1 3301.85
   285.4 3302.43   301.4 3304.83   321.7 3303.88   346.2 3304.47   368.2 3304.18
   405.9 3305.12   435.7 3307.64   448.4 3307.67   479.2 3310.47   510.1 3312.29
#Mann= 7 ,-1,0
       0     .06       0      60     .08       0  161.22      .1       0
  259.08     .06       0   267.4    .045       0   285.4     .06       0
  461.48     .12       0
#XS Ineff= 2 , 0
                          344.85         3308.37
Permanent Ineff=
       F       F
Bank Sta=267.4,285.4
XS Rating Curve= 0 ,0
Exp/Cntr(USF)=0,0
Exp/Cntr=0.3,0.1

Type RM Length L Ch R = 1 ,4791    ,86.7,68.7,53.4
BEGIN DESCRIPTION:
structure xs 4
END DESCRIPTION:
XS GIS Cut Line= 5
2154162.74429681434693.089073383 2154160.4724518434826.656282717
2154142.10495621434876.1337952482154206.78330334434953.552775895
2154356.03707047435259.762572921
#Sta/Elev= 30
       0 3316.54     8.1 3316.31    16.1 3314.83    24.1 3310.37    53.8 3310.67
   112.1 3307.99   127.7 3308.77   153.3 3308.51   157.6 3307.78  165.83 3302.63
     170 3301.46   176.2 3302.62   183.2 3303.88   203.4 3303.79     219  3304.9
   234.6 3304.01   255.5 3305.42   304.6 3304.28     318 3303.31   326.9 3304.53
   344.7 3304.52     358 3305.64   377.8 3303.69   415.9 3304.12   428.6 3306.27
   445.6 3305.25   500.4 3307.34   549.4 3311.66   571.6 3311.86   627.9 3315.98
#Mann= 10 ,-1,0
       0     .06       0      70     .08       0  165.83    .045       0
   176.2     .06       0  256.36      .1       0  297.24     .06       0
  407.24     .12       0  457.24     .06       0  507.24     .12       0
  617.24      .1       0
#XS Ineff= 2 , 0
                          362.79         3310.67
Permanent Ineff=
       F       F
Bank Sta=165.83,176.2
XS Rating Curve= 0 ,0
Exp/Cntr(USF)=0,0
Exp/Cntr=0.5,0.3

Type RM Length L Ch R = 1 ,4741    ,23,27.1,27.5
BEGIN DESCRIPTION:
structure xs 3; 14.9 ft between structure and xs
END DESCRIPTION:
XS GIS Cut Line= 5
2154000.05197736434769.8864072362154059.24101097434872.850663626
2154173.78850768434936.1093355632154210.67370819434966.002835148
2154326.74204383435271.878419864
#Sta/Elev= 30
       0 3312.22    90.4  3308.2   124.4 3307.48     129 3306.47137.29983302.063
   147.2 3301.49     155    3302   163.8 3303.43   183.8 3302.88   210.9 3303.97
   220.4 3303.62   234.1 3305.21   243.2 3304.75   252.1  3305.4   270.4 3305.03
   286.2  3304.4   300.5 3304.12   309.1 3303.29   321.9 3304.48     339 3304.38
   351.8 3305.48   377.5 3304.21   398.9 3304.58   411.7 3306.42   459.2 3305.97
   499.2 3307.07   544.4 3310.34   591.4 3311.55   607.8 3312.52   624.3 3312.67
#Mann= 7 ,-1,0
       0     .06       0137.2998    .045       0     155     .06       0
   270.4      .1       0   286.2     .06       0   398.9     .12       0
   607.8      .1       0
#XS Ineff= 3 ,-1
       0     122 3305.13     170     347 3303.94     347     618    3310
Permanent Ineff=
       F       F       F
Bank Sta=137.2998,155
XS Rating Curve= 0 ,0
Exp/Cntr(USF)=0,0
Exp/Cntr=0.5,0.3

Type RM Length L Ch R = 1 ,4714    ,66.4,66,65.4
BEGIN DESCRIPTION:
structure xs 2; 4.8 ft between structure and xs
END DESCRIPTION:
XS GIS Cut Line= 4
2153963.40936102434773.7130203082154044.79428223  434889.6248778
2154212.61118486434992.5420530462154302.35269799435287.000075714
#Sta/Elev= 30
       0 3312.45     9.1    3311    40.4 3310.81    97.1 3308.07   112.7 3308.01
   140.9 3306.09   150.3 3305.27158.39693302.186   161.2 3301.71 168.6953302.205
   193.2 3303.63   217.3 3302.26   248.8 3302.96   272.3 3305.42   292.1 3304.55
   309.1 3302.74   343.3 3304.12   355.9 3305.29   385.2 3304.78   397.7 3306.83
   409.2 3307.22   422.8  3307.6   435.3 3306.44   474.2 3306.03   492.5 3306.68
   502.2 3307.82   534.2 3307.93   610.8 3310.39   636.1 3311.16   646.3 3312.19
#Mann= 6 ,-1,0
       0      .1       0    40.4     .06       0158.3969    .045       0
 168.695     .06       0   409.2     .12       0   610.8      .1       0
#XS Ineff= 3 ,-1
       0   156.7 3305.13   170.2  355.81 3303.94  355.81   531.4 3308.09
Permanent Ineff=
       F       F       F
Bank Sta=158.3969,168.695
XS Rating Curve= 0 ,0
Exp/Cntr(USF)=0,0
Exp/Cntr=0.5,0.3

Type RM Length L Ch R = 1 ,4648    ,123.6,124.6,126.8
BEGIN DESCRIPTION:
structure xs 1
END DESCRIPTION:
XS GIS Cut Line= 4
2153937.53051236434785.1573466592153940.62954627434910.668219888
2154131.54076664435008.4135014022154290.82037775435289.525115005
#Sta/Elev= 30
       0 3310.94      16 3309.92      56 3309.05      68 3307.93      84 3308.47
   120.1 3306.87   131.1 3305.74     143 3302.52   147.5 3302.23     170  3303.5
   205.9 3304.08   219.2 3301.05   222.83300.838   225.2 3300.76   237.73300.882
   246.4 3303.17   269.7 3304.26   286.8 3303.95   295.8 3302.65   320.3    3303
   340.9 3306.93   354.7 3308.39   363.9 3307.61   440.8 3307.22     463 3305.86
   490.7 3306.04   543.5 3307.44   570.8 3309.04   609.1 3309.38   663.1 3312.32
#Mann= 7 ,-1,0
       0      .1       0  185.55     .06       0   222.8    .045       0
   237.7      .1       0  295.55     .06       0  400.03     .12       0
  650.03      .1       0
Bank Sta=222.8,237.7
XS Rating Curve= 0 ,0
Exp/Cntr(USF)=0,0
Exp/Cntr=0.3,0.1

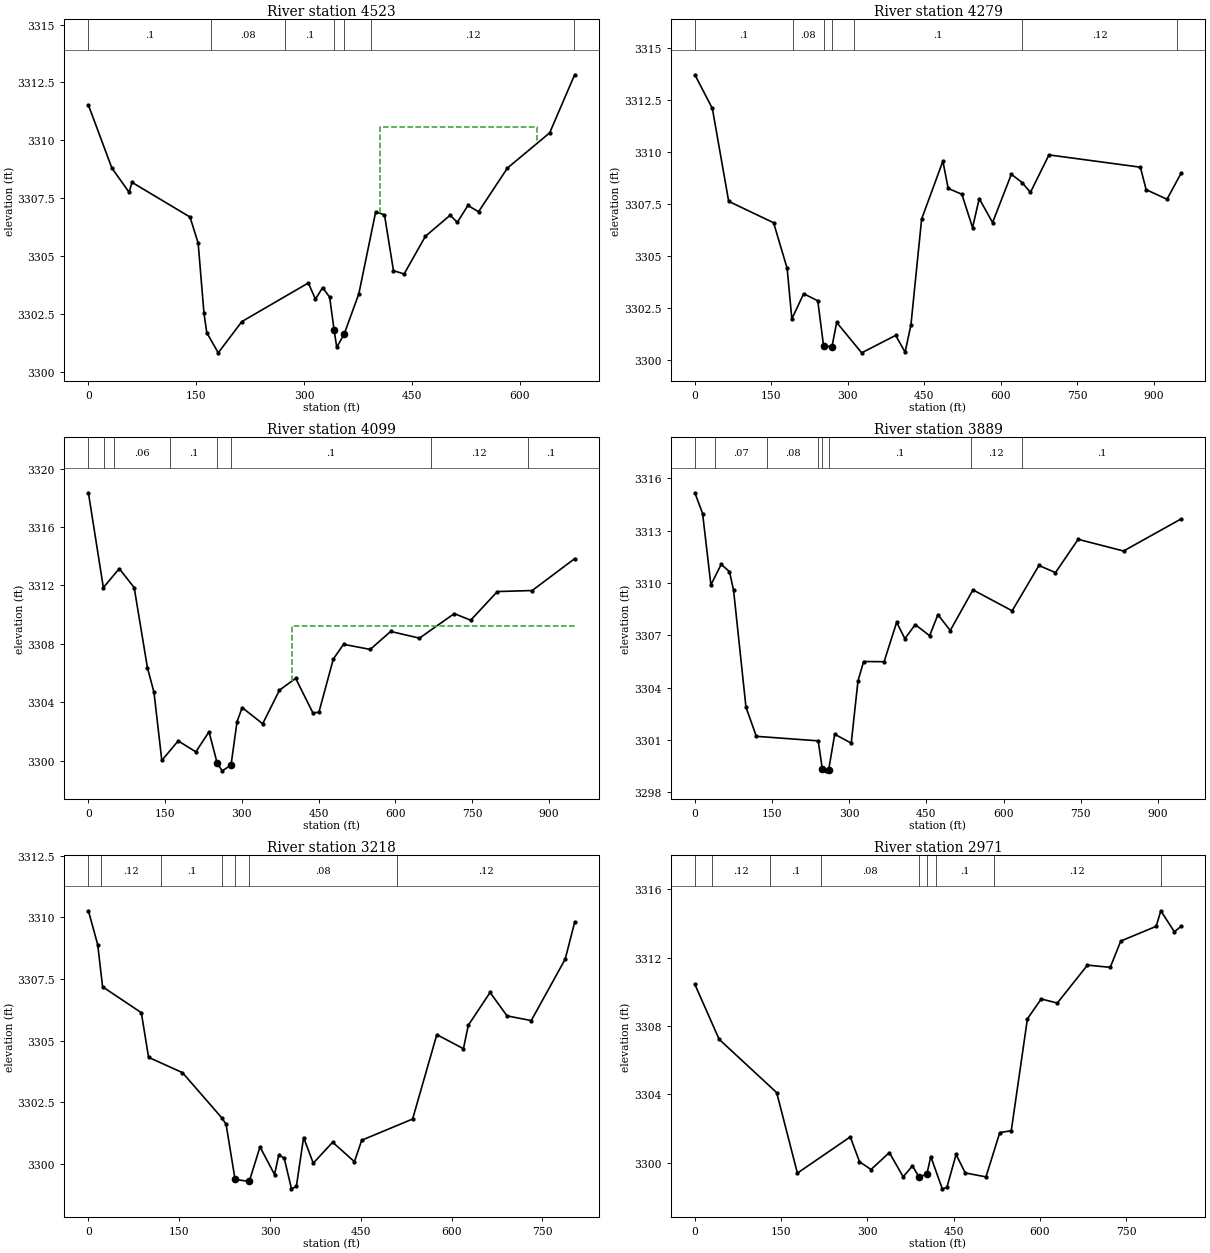
Type RM Length L Ch R = 1 ,4523    ,224.6,243.6,260.7
XS GIS Cut Line= 4
2153922.59928769434792.5829500142153920.29560636434975.275199307
 2154230.7451141435199.0937720312154285.18052845435295.479413956
#Sta/Elev= 30
       0 3311.52    32.6  3308.8    56.6 3307.75    60.6 3308.18   141.3 3306.68
   152.6 3305.55   160.6 3302.55   164.6 3301.68   180.5 3300.81   213.3 3302.16
   305.8 3303.83   315.7 3303.13   325.6 3303.63   335.4 3303.22341.68193301.789
   345.3 3301.05355.58143301.616     376 3303.36   399.5 3306.91   411.7 3306.77
   424.2 3304.36     439 3304.22   468.6 3305.85   503.1 3306.76   512.9 3306.45
   527.7 3307.18   542.5 3306.91   582.7  3308.8   641.4 3310.32   676.1 3312.83
#Mann= 7 ,-1,0
       0      .1       0     170     .08       0  272.71      .1       0
341.6819    .045       0355.5814      .1       0  392.71     .12       0
  675.43      .1       0
#XS Ineff= 1 ,-1
  405.41     6243310.565
Permanent Ineff=
       F
Bank Sta=341.6819,355.5814
XS Rating Curve= 0 ,0
Exp/Cntr(USF)=0,0
Exp/Cntr=0.3,0.1

Type RM Length L Ch R = 1 ,4279    ,181.3,180.1,177.7
XS GIS Cut Line= 5
2153902.62533575434766.8300815762153901.89162243434928.487664852
2153725.59840751435231.2364126882153667.69488136435362.774652128
2153716.30176902435656.908638978
#Sta/Elev= 30
       0 3313.71    34.3 3312.09    66.3 3307.63   154.4  3306.6     181 3304.41
   190.2 3301.98   213.4 3303.19   241.1 3302.85   252.5 3300.67   268.9 3300.65
   278.2 3301.81   327.2 3300.35   393.9 3301.19   412.4 3300.38   423.8 3301.69
   444.8 3306.78   486.5 3309.56   496.9 3308.25   523.7 3307.97   544.7 3306.37
   557.8 3307.76     584 3306.61   620.8 3308.93     642 3308.53   658.2 3308.06
   694.6 3309.86   873.9 3309.27   885.2 3308.19   926.1 3307.73   953.8 3308.98
#Mann= 7 ,-1,0
       0      .1       0  191.66     .08       0   252.5    .045       0
   268.9     .08       0  311.66      .1       0     642     .12       0
  945.72      .1       0
Bank Sta=252.5,268.9
XS Rating Curve= 0 ,0
Exp/Cntr(USF)=0,0
Exp/Cntr=0.3,0.1

Type RM Length L Ch R = 1 ,4099    ,213.5,210.8,195.3
XS GIS Cut Line= 3
2153799.33810318434714.0256570562153655.75276692435075.910632108
2153618.82445721435635.989996062
#Sta/Elev= 30
       0 3318.34    29.2 3311.85    60.3 3313.15    89.5 3311.85   115.3 3306.38
   128.2 3304.68   143.5 3300.02   175.5 3301.36     210 3300.61   235.8 3301.98
251.90463299.815   261.6 3299.31   278.8  3299.7   290.6 3302.68   300.6 3303.64
   340.7 3302.53   373.5 3304.83   405.2 3305.64     439 3303.27   450.7 3303.33
   478.8 3306.96   498.8 3307.97   550.9 3307.62     591 3308.85   647.2 3308.39
   715.3 3310.07   747.4 3309.62   799.5 3311.58   867.6 3311.65   950.6 3313.83
#Mann= 8 ,-1,0
       0     .06       0      30      .1       0      50     .06       0
     160      .1       0251.9046    .045       0   278.8      .1       0
  669.33     .12       0  859.33      .1       0
#XS Ineff= 1 ,-1
  398.67  950.983309.218
Permanent Ineff=
       F
Bank Sta=251.9046,278.8
XS Rating Curve= 0 ,0
Exp/Cntr(USF)=0,0
Exp/Cntr=0.3,0.1

Type RM Length L Ch R = 1 ,3889    ,654.2,670.3,665.7
XS GIS Cut Line= 3
2153581.54863265434718.2060532412153554.66348005435053.053841221
2153513.11913163435660.832271885
#Sta/Elev= 30
       0 3315.18      15 3313.99    31.1  3309.9    51.1 3311.07    67.2 3310.66
    75.2 3309.59    99.3 3302.88   119.4 3301.21   239.7 3300.95247.79813299.321
   255.8 3299.23 259.798 3299.25   271.8 3301.33   303.9 3300.82     317 3304.38
     328  3305.5   367.8 3305.49   392.2 3307.75   408.2 3306.81   428.3 3307.62
   456.3 3306.98   472.4 3308.19   496.4 3307.28   540.5 3309.61   616.7 3308.41
   668.8 3311.01   700.9  3310.6     745 3312.51   833.2 3311.84   945.1 3313.68
#Mann= 8 ,-1,0
       0     .06       0      40     .07       0     140     .08       0
     240      .1       0247.7981    .045       0 259.798      .1       0
  535.93     .12       0  635.93      .1       0
Bank Sta=247.7981,259.798
XS Rating Curve= 0 ,0
Exp/Cntr(USF)=0,0
Exp/Cntr=0.3,0.1

Type RM Length L Ch R = 1 ,3218    ,245.8,247.3,249.3
XS GIS Cut Line= 2
 2153214.4839864434741.8349846862153236.96695135435544.858414996
#Sta/Elev= 30
       0 3310.27    15.4 3308.89    23.4 3307.19    87.4 3306.14    99.4 3304.33
   155.4 3303.71   219.9 3301.89   227.4 3301.62   242.3 3299.38   265.7  3299.3
   283.5  3300.7   307.5 3299.58   314.6 3300.38   323.5 3300.24   335.5    3299
   343.6  3299.1   355.5 3301.08   371.5 3300.04   403.5 3300.89   439.5  3300.1
   451.5 3300.97   535.6 3301.83   575.6 3305.25   619.6 3304.68   627.6 3305.63
   663.6 3306.96   691.6 3306.01   731.6 3305.82   787.7 3308.31   803.3  3309.8
#Mann= 7 ,-1,0
       0     .06       0      20     .12       0     120      .1       0
     220     .08       0   242.3    .045       0   265.7     .08       0
     510     .12       0
Bank Sta=242.3,265.7
XS Rating Curve= 0 ,0
Exp/Cntr(USF)=0,0
Exp/Cntr=0.3,0.1

Type RM Length L Ch R = 1 ,2971    ,221.4,233.4,233.1
XS GIS Cut Line= 2
2153110.09205277434734.9527530932153092.36809286435580.500027711
#Sta/Elev= 30
       0 3310.43    42.2 3307.22   142.3  3304.1   178.3 3299.39   270.3 3301.51
   286.3 3300.06   306.3  3299.6   338.3 3300.59   362.3 3299.17   378.3 3299.81
390.09443299.159403.49483299.332   410.3 3300.36   430.3 3298.47   438.3 3298.55
   454.3 3300.48   470.3  3299.4   506.3 3299.17   530.3 3301.76   550.3 3301.87
   578.4 3308.42   602.4 3309.58   630.4 3309.34   682.8 3311.56   722.4 3311.43
   740.8 3312.97   802.4 3313.83   810.4 3314.74     834 3313.51   845.7 3313.83
#Mann= 9 ,-1,0
       0     .06       0      30     .12       0     130      .1       0
     220     .08       0390.0944    .045       0403.4948     .08       0
     420      .1       0     520     .12       0     810      .1       0
Bank Sta=390.0944,403.4948
XS Rating Curve= 0 ,0
Exp/Cntr(USF)=0,0
Exp/Cntr=0.3,0.1

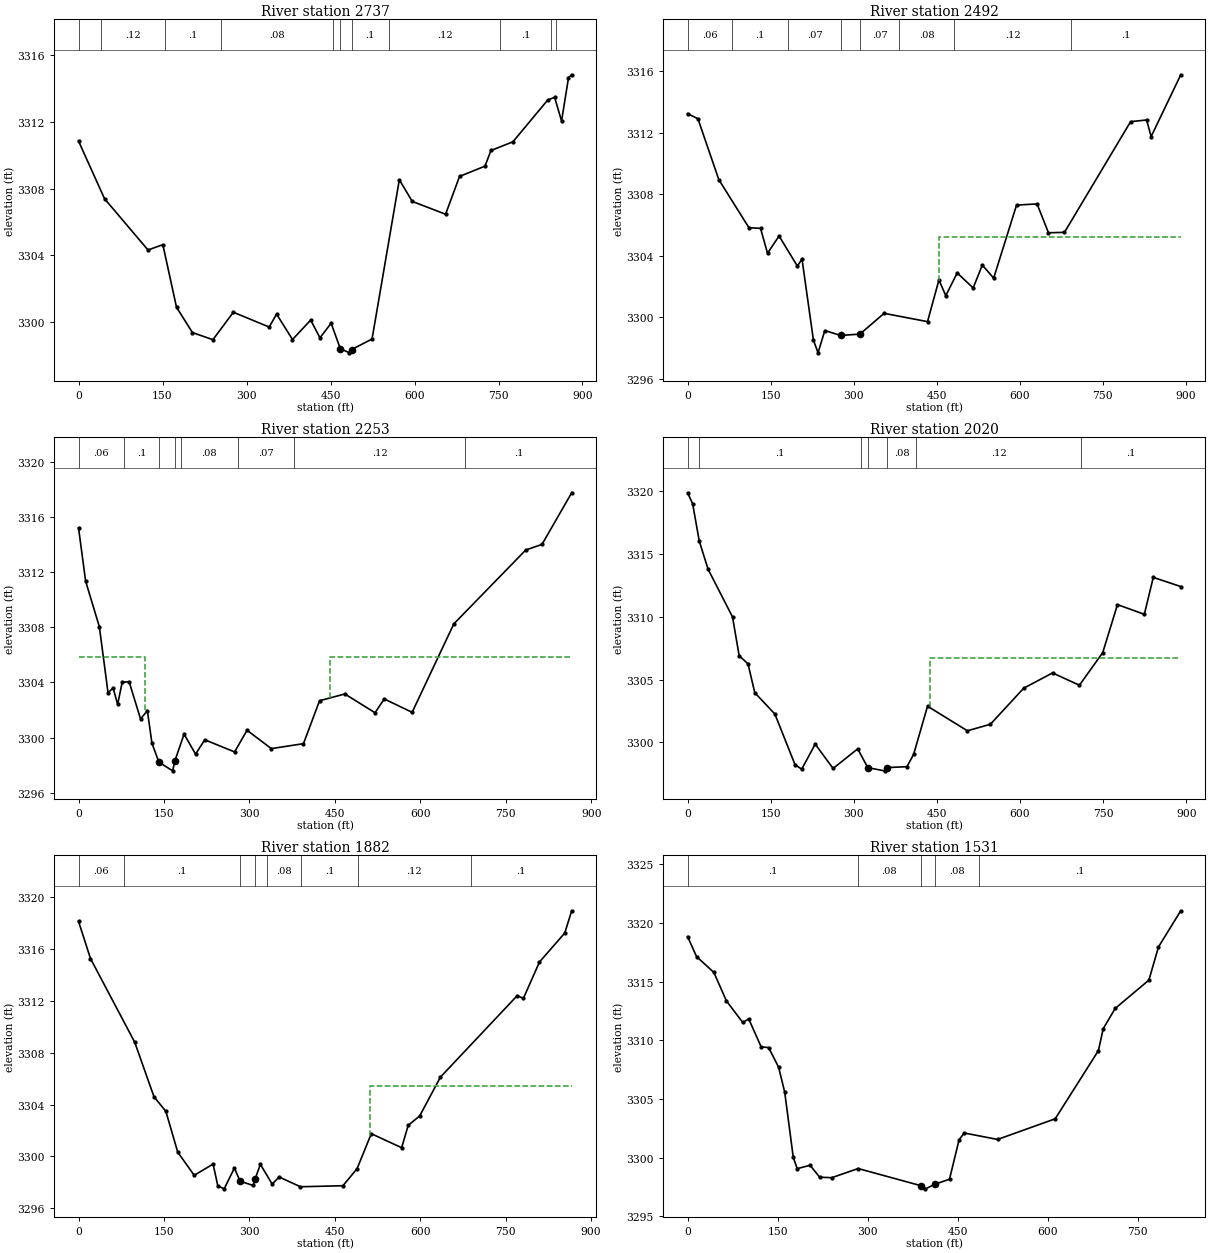
Type RM Length L Ch R = 1 ,2737    ,246.4,245.3,238.3
XS GIS Cut Line= 4
2153079.21149252434728.3924516762153009.97091181434854.564176523
2152934.40464842435287.4460292492153011.33862699435574.666215892
#Sta/Elev= 30
       0 3310.86    46.5 3307.39   124.1 3304.31   150.6 3304.63     175 3300.87
   203.4 3299.35     240 3298.92   276.5 3300.57   340.5 3299.68   353.7 3300.46
   382.1 3298.93   414.6  3300.1   431.2 3299.03   451.1 3299.91   467.4 3298.39
   483.6 3298.13   487.7 3298.33   524.2 3298.96   572.9 3308.53     596 3307.23
   655.5 3306.46   680.4 3308.73   725.9 3309.35   736.5 3310.29   775.7 3310.81
   837.8 3313.32   850.2 3313.49   862.6 3312.06     875 3314.66   880.7 3314.84
#Mann= 11 ,-1,0
       0     .07       0      40     .12       0  153.92      .1       0
  253.92     .08       0  453.92      .1       0   467.4    .045       0
   487.7      .1       0  553.92     .12       0  753.35      .1       0
  843.35     .12       0  853.35      .1       0
Bank Sta=467.4,487.7
XS Rating Curve= 0 ,0
Exp/Cntr(USF)=0,0
Exp/Cntr=0.3,0.1

Type RM Length L Ch R = 1 ,2492    ,215.7,239.2,214.4
XS GIS Cut Line= 3
2152954.92037604434687.360996441  2152903.631057 434851.48681738
2152729.24737225 435549.02155637
#Sta/Elev= 30
       0 3313.25    18.7 3312.92    56.4 3308.96   110.9 3305.83   131.8 3305.79
   144.4 3304.17   165.3 3305.29   198.4 3303.33   206.7  3303.8   227.3 3298.53
   235.7 3297.69   247.9 3299.14   276.8 3298.82   311.4 3298.91   355.1 3300.26
   433.5 3299.72   454.1 3302.43   466.5 3301.41   487.1 3302.89   515.9 3301.91
   532.5  3303.4     553 3302.55   594.3  3307.3   631.4 3307.38     652  3305.5
   680.9 3305.53   800.4 3312.73   829.3 3312.84   837.5 3311.76     891 3315.78
#Mann= 8 ,-1,0
       0     .06       0      80      .1       0  181.95     .07       0
   276.8    .045       0   311.4     .07       0  381.95     .08       0
  481.95     .12       0  691.95      .1       0
#XS Ineff= 2 , 0
                          454.65         3305.23
Permanent Ineff=
       F       F
Bank Sta=276.8,311.4
XS Rating Curve= 0 ,0
Exp/Cntr(USF)=0,0
Exp/Cntr=0.3,0.1

Type RM Length L Ch R = 1 ,2253    ,229.1,233.1,224.7
XS GIS Cut Line= 4
 2152777.6364941434684.7691291222152765.11737257434823.337616274
2152725.82808431435140.4166479912152650.60374972 435540.47333653
#Sta/Elev= 30
       0 3315.21    12.5 3311.33    36.6 3308.03    51.8 3303.25    60.7 3303.59
    68.7 3302.41    76.7 3304.01    88.8 3304.05   108.9 3301.35   120.9 3301.95
   128.9 3299.59 141.131 3298.22   165.2 3297.59   169.2 3298.32   185.3 3300.25
   205.5  3298.8   221.6 3299.84     274 3298.96   295.8 3300.53   338.5  3299.2
   394.9 3299.56   423.1 3302.67   467.5 3303.16   520.5  3301.8   536.7  3302.8
   585.6 3301.83   658.8 3308.24     785 3313.59   813.6    3314   865.7 3317.74
#Mann= 8 ,-1,0
       0     .06       0      80      .1       0 141.131    .045       0
   169.2      .1       0  179.13     .08       0  279.13     .07       0
  379.13     .12       0  678.64      .1       0
#XS Ineff= 2 ,-1
       0   116.9 3305.86  441.69   862.1 3305.86
Permanent Ineff=
       F       F
Bank Sta=141.131,169.2
XS Rating Curve= 0 ,0
Exp/Cntr(USF)=0,0
Exp/Cntr=0.3,0.1

Type RM Length L Ch R = 1 ,2020    ,136.6,137.6,128.9
XS GIS Cut Line= 4
2152589.55479576434648.0391851752152588.58616747 434760.72394533
  2152635.216954435094.2562608522152571.96012718435530.215472721
#Sta/Elev= 30
       0 3319.88     9.1 3319.01    21.1 3316.03    37.1 3313.78    81.1 3309.99
    93.1  3306.9   109.1 3306.25   121.2 3303.96   157.6 3302.25   193.9 3298.22
     206 3297.86   230.3 3299.86   262.6 3297.92     307 3299.48   325.3 3297.98
   355.5 3297.73   359.5 3297.99   395.9 3298.06     408 3299.05     433 3302.88
     505 3300.92   546.5 3301.44   606.5 3304.31   658.6 3305.53   707.1 3304.55
   749.2 3307.15   775.8 3310.97   824.3  3310.2   840.4 3313.14     890 3312.41
#Mann= 7 ,-1,0
       0     .06       0      20      .1       0  312.69     .08       0
   325.3    .045       0   359.5     .08       0  412.69     .12       0
  709.47      .1       0
#XS Ineff= 1 ,-1
  436.62   887.4 3306.71
Permanent Ineff=
       F
Bank Sta=325.3,359.5
XS Rating Curve= 0 ,0
Exp/Cntr(USF)=0,0
Exp/Cntr=0.3,0.1

Type RM Length L Ch R = 1 ,1882    ,324.8,351.3,328.1
XS GIS Cut Line= 4
2152414.67288212434683.9417085052152460.83326925434817.293938018
2152559.99261941435181.4481032262152508.70330036435525.086540817
#Sta/Elev= 30
       0 3318.12      21 3315.25    98.7  3308.8   132.5  3304.6   153.4 3303.47
   174.2 3300.33   203.2 3298.54   236.3 3299.41   244.6 3297.73   255.8  3297.5
   273.7  3299.1   283.9 3298.08   306.8 3297.76   309.9 3298.23   319.3 3299.39
     340 3297.87   352.4 3298.41   389.7 3297.66   464.4 3297.74   489.2 3299.06
   514.1 3301.75   567.4 3300.67   578.9 3302.39   599.1 3303.12   635.5 3306.11
   770.4 3312.39   781.1 3312.17   809.4 3314.98   853.9 3317.22     866 3318.93
#Mann= 8 ,-1,0
       0     .06       0      80      .1       0   283.9    .045       0
   309.9      .1       0  331.12     .08       0  391.12      .1       0
  491.12     .12       0  688.53      .1       0
#XS Ineff= 2 , 0
                          512.11          3305.4
Permanent Ineff=
       F       F
Bank Sta=283.9,309.9
XS Rating Curve= 0 ,0
Exp/Cntr(USF)=0,0
Exp/Cntr=0.3,0.1

Type RM Length L Ch R = 1 ,1531    ,143.6,146.6,148
XS GIS Cut Line= 4
  2152313.803888434678.8127766012152356.52981303434836.297285929
 2152371.8255637435138.570436457 2152361.6739191435494.312949391
#Sta/Elev= 30
       0 3318.84    14.9 3317.14    43.9 3315.78    64.6 3313.37    91.9 3311.52
   101.9 3311.82   122.6 3309.44   135.1 3309.38   151.7  3307.7   161.8 3305.59
   176.1 3300.02   182.7 3299.06   204.1 3299.35   220.1 3298.33   240.2 3298.29
   284.2 3299.07   388.6 3297.61   396.4 3297.34   412.4 3297.74   436.4 3298.16
   452.4 3301.53     461  3302.1   516.5 3301.55   612.5 3303.31   684.5 3309.12
   692.5 3310.99   712.5 3312.72   768.6 3315.13   784.6 3317.96   821.7 3321.04
#Mann= 5 ,-1,0
       0      .1       0  283.18     .08       0   388.6    .045       0
   412.4     .08       0  485.84      .1       0
Bank Sta=388.6,412.4
XS Rating Curve= 0 ,0
Exp/Cntr(USF)=0,0
Exp/Cntr=0.3,0.1