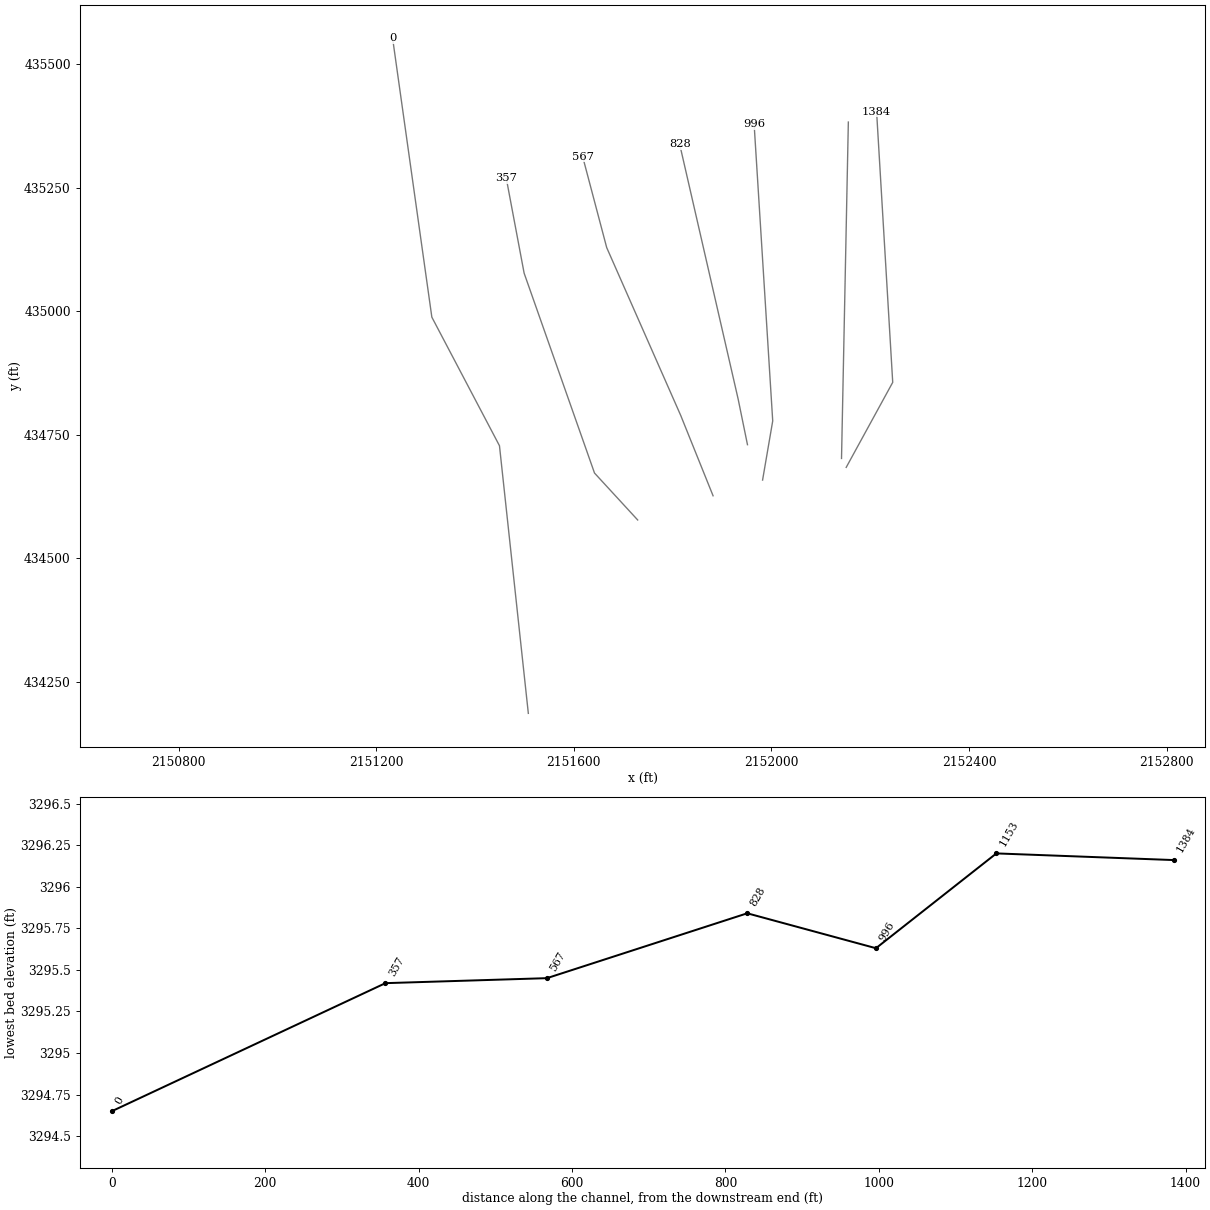
HEC-RAS study NFCHRYRV.prj: NFCHRYRV

--- NFCHRYRV.g01 (geometry) --- (continued)

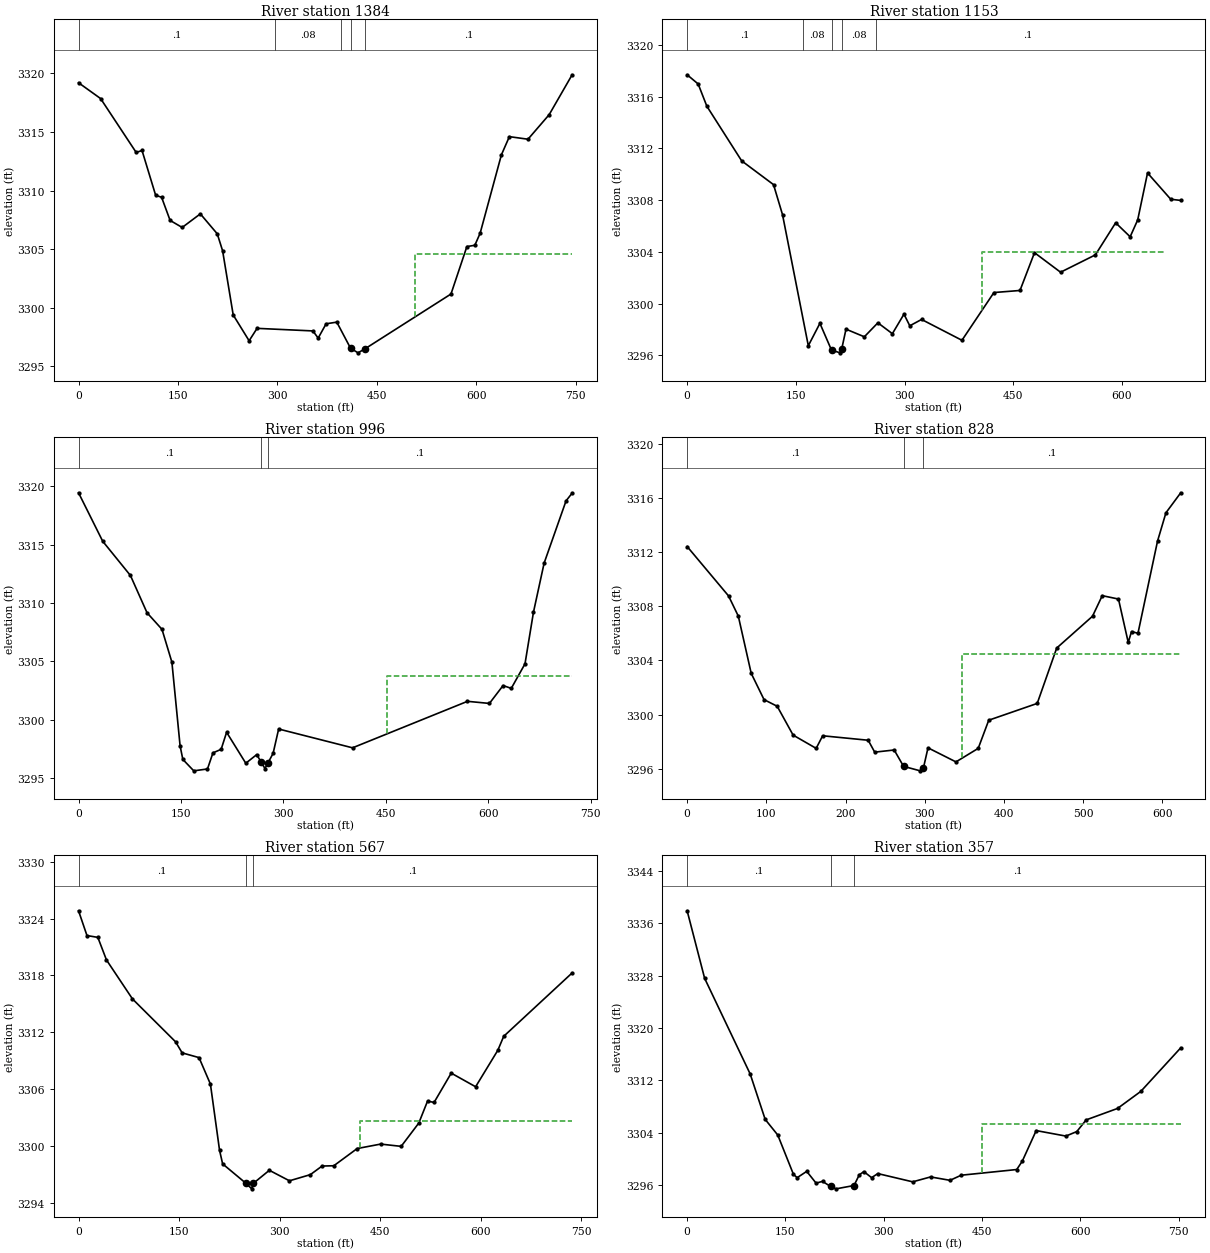
Type RM Length L Ch R = 1 ,1384    ,226.8,231,234.2
XS GIS Cut Line= 3
2152151.38771103434683.941708505 2152245.5640996434856.049922692
2152212.93489388435403.701819081
#Sta/Elev= 30
       0 3319.21    33.3 3317.86      87 3313.26    95.8 3313.43   116.4  3309.6
   125.3 3309.44   138.2 3307.46   156.4 3306.86   183.8 3308.02   209.3 3306.32
   217.4 3304.87   233.4 3299.39   257.4 3297.19   269.4 3298.25   353.6 3298.03
   361.6 3297.42   373.6 3298.64   389.7 3298.78   410.4 3296.56   421.7 3296.16
     433 3296.53     562 3301.18     586 3305.23     598 3305.34     606 3306.37
   638.1 3313.06   650.1 3314.61   678.2 3314.39   710.2 3316.49   744.8 3319.89
#Mann= 5 ,-1,0
       0      .1       0  296.19     .08       0  396.19      .1       0
   410.4    .045       0     433      .1       0
#XS Ineff= 2 , 0
                          507.49         3304.63
Permanent Ineff=
       F       F
Bank Sta=410.4,433
XS Rating Curve= 0 ,0
Exp/Cntr(USF)=0,0
Exp/Cntr=0.3,0.1

Type RM Length L Ch R = 1 ,1153    ,156.1,157,157.3
XS GIS Cut Line= 2
2152141.91556539 434702.00814318 2152155.7321956435382.955110016
#Sta/Elev= 30
       0 3317.69    15.2 3316.98    27.2 3315.26    75.2 3311.04   119.2  3309.2
   131.6 3306.88   167.2 3296.75   183.2 3298.48   199.2 3296.41   211.2  3296.2
   213.2 3296.47   219.2 3298.03   244.5 3297.44   263.2 3298.52   283.2 3297.68
   299.2 3299.19   307.2 3298.29   323.5 3298.78   379.2 3297.17   423.3 3300.86
   459.3 3301.02   479.3 3303.94   515.3 3302.43   563.3 3303.77   591.3 3306.25
   611.3 3305.17   621.7 3306.47   635.3  3310.1   667.3 3308.07   681.1 3307.98
#Mann= 5 ,-1,0
       0      .1       0     160     .08       0   199.2    .045       0
   213.2     .08       0     260      .1       0
#XS Ineff= 1 ,-1
  406.59   658.9 3303.98
Permanent Ineff=
       F
Bank Sta=199.2,213.2
XS Rating Curve= 0 ,0
Exp/Cntr(USF)=0,0
Exp/Cntr=0.3,0.1

Type RM Length L Ch R = 1 ,996     ,155.4,167.8,174.1
XS GIS Cut Line= 3
2151982.13295818434658.297048983 2152002.6486858434777.972126751
 2151965.0365185435378.057159559
#Sta/Elev= 30
       0 3319.43    35.4 3315.28      76 3312.35   100.3 3309.16   122.2 3307.74
   136.7 3304.93   148.7 3297.77   152.7 3296.61   168.7 3295.63   188.8 3295.79
   196.8 3297.17   208.8 3297.47   216.8 3298.93   244.9 3296.28   260.9 3297.02
   267.6 3296.36   272.9 3295.83   277.6 3296.33   284.9 3297.13     293 3299.21
   401.2  3297.6   569.5 3301.58   601.6  3301.4   621.6 3302.93   633.6 3302.69
   653.7 3304.79   666.1 3309.21   681.7 3313.41   713.8 3318.74   722.7  3319.4
#Mann= 3 ,-1,0
       0      .1       0   267.6    .045       0   277.6      .1       0
#XS Ineff= 2 , 0
                          451.61         3303.73
Permanent Ineff=
       F       F
Bank Sta=267.6,277.6
XS Rating Curve= 0 ,0
Exp/Cntr(USF)=0,0
Exp/Cntr=0.3,0.1

Type RM Length L Ch R = 1 ,828     ,243.5,261.2,261.3
XS GIS Cut Line= 3
 2151951.5493272434729.8910284872151932.55328311434822.760577372
2151814.35567544435337.764439372
#Sta/Elev= 30
       0 3312.41    52.3 3308.76    64.6 3307.27    80.9 3303.04    97.1  3301.1
   113.7 3300.61   133.8 3298.48   162.9  3297.5   171.1 3298.43   228.6  3298.1
   236.8 3297.22   261.4 3297.38   273.3 3296.17   294.3 3295.84   298.4 3296.07
   304.1 3297.54   339.4  3296.5   367.5  3297.5   380.8 3299.58     442 3300.82
   466.6 3304.91   511.8 3307.26   524.1 3308.78   544.6 3308.53   556.9 3305.33
   561.1 3306.13   569.2    3306   593.9 3312.81   604.5  3314.9   623.2 3316.38
#Mann= 3 ,-1,0
       0      .1       0   273.3    .045       0   298.4      .1       0
#XS Ineff= 2 , 0
                          347.04         3304.44
Permanent Ineff=
       F       F
Bank Sta=273.3,298.4
XS Rating Curve= 0 ,0
Exp/Cntr(USF)=0,0
Exp/Cntr=0.3,0.1

Type RM Length L Ch R = 1 ,567     ,217.5,210.5,205.8
XS GIS Cut Line= 4
2151881.89716553434626.468121774  2151816.466347434788.989832323
2151666.60866584 435128.807954382151618.06321984435312.436380585
#Sta/Elev= 30
       0 3324.84    12.6 3322.22    28.8 3322.03    41.7 3319.64    80.5 3315.52
   144.8 3310.99   154.6 3309.82   179.8 3309.32   196.8 3306.52   210.4 3299.53
     215 3298.09   249.7 3296.04   258.5 3295.45     261 3296.04   284.7 3297.41
   314.7  3296.3   345.9 3296.95   363.4 3297.86   380.9 3297.89   415.8 3299.71
   450.8 3300.18   481.4 3299.94   507.7  3302.4   520.8 3304.73   530.5 3304.58
   556.1 3307.68   592.5 3306.24   625.6 3310.09   634.4 3311.57   736.5 3318.27
#Mann= 3 ,-1,0
       0      .1       0   249.7    .045       0     261      .1       0
#XS Ineff= 2 , 0
                          420.06         3302.63
Permanent Ineff=
       F       F
Bank Sta=249.7,261
XS Rating Curve= 0 ,0
Exp/Cntr(USF)=0,0
Exp/Cntr=0.3,0.1

Type RM Length L Ch R = 1 ,357     ,356.8,356.8,356.8
XS GIS Cut Line= 4
2151729.29561134434577.5005414532151641.91380853434672.480761904
2151499.44347785435077.0965010242151463.35099408435268.956546334
#Sta/Elev= 30
       0  3337.9    26.7 3327.58    96.2 3312.97   119.1 3306.03   138.3 3303.64
   162.3 3297.62     168 3297.13   182.5 3298.09   196.8 3296.29   206.6 3296.56
   218.9 3295.78   227.3 3295.42   254.7 3295.93   262.7 3297.56   269.7 3298.05
   281.5 3297.13     291 3297.75   344.2 3296.49   371.5 3297.24   401.2 3296.72
   418.2  3297.5     503 3298.37   511.5 3299.65   532.7 3304.32     578 3303.48
   594.7 3304.17   608.9 3305.95   656.8  3307.7   692.4 3310.31   753.3 3316.96
#Mann= 3 ,-1,0
       0      .1       0   218.9    .045       0   254.7      .1       0
#XS Ineff= 2 , 0
                           450.7         3305.39
Permanent Ineff=
       F       F
Bank Sta=218.9,254.7
XS Rating Curve= 0 ,0
Exp/Cntr(USF)=0,0
Exp/Cntr=0.3,0.1

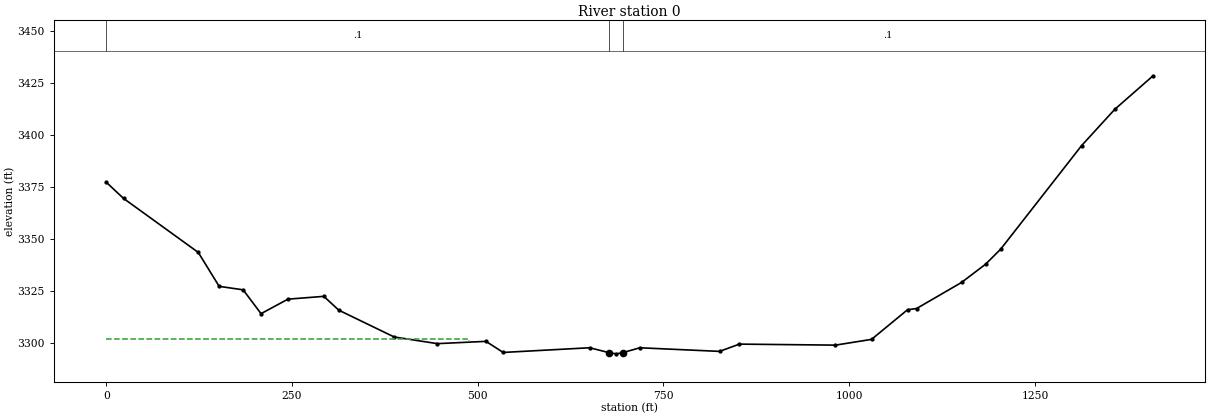
Type RM Length L Ch R = 1 ,0       ,1441.4,1484.8,1429.7
XS GIS Cut Line= 4
     2151507.961      434186.007      2151449.53      434727.786
     2151312.652      434988.024     2151233.229      435552.436
#Sta/Elev= 30
       0 3377.27    23.3 3369.47   123.9 3343.47     152 3327.14   184.3 3325.46
   208.4 3313.99   244.6 3320.97   292.9 3322.32     313 3315.67   387.6 3302.76
   445.7 3299.56   511.1 3300.66   534.3 3295.32   650.6 3297.58   677.3 3295.17
   686.6 3294.65     695  3295.2   718.2 3297.57   825.4 3295.83   852.2 3299.33
   981.5 3298.84    1030 3301.61  1078.5 3315.89  1090.6 3316.45  1151.2 3329.03
  1183.5  3337.8  1203.7 3344.99  1312.7 3394.88  1357.4 3412.36  1408.9 3428.49
#Mann= 3 ,-1,0
       0      .1       0   677.3    .045       0     695      .1       0
#XS Ineff= 2 , 0
           488.7 3301.92
Permanent Ineff=
       F       F
Bank Sta=677.3,695
XS Rating Curve= 0 ,0
Exp/Cntr=0.3,0.1
LCMann Table=0

Chan Stop Cuts=-1
Use User Specified Reach Order=0
Composite Channel Slope=5